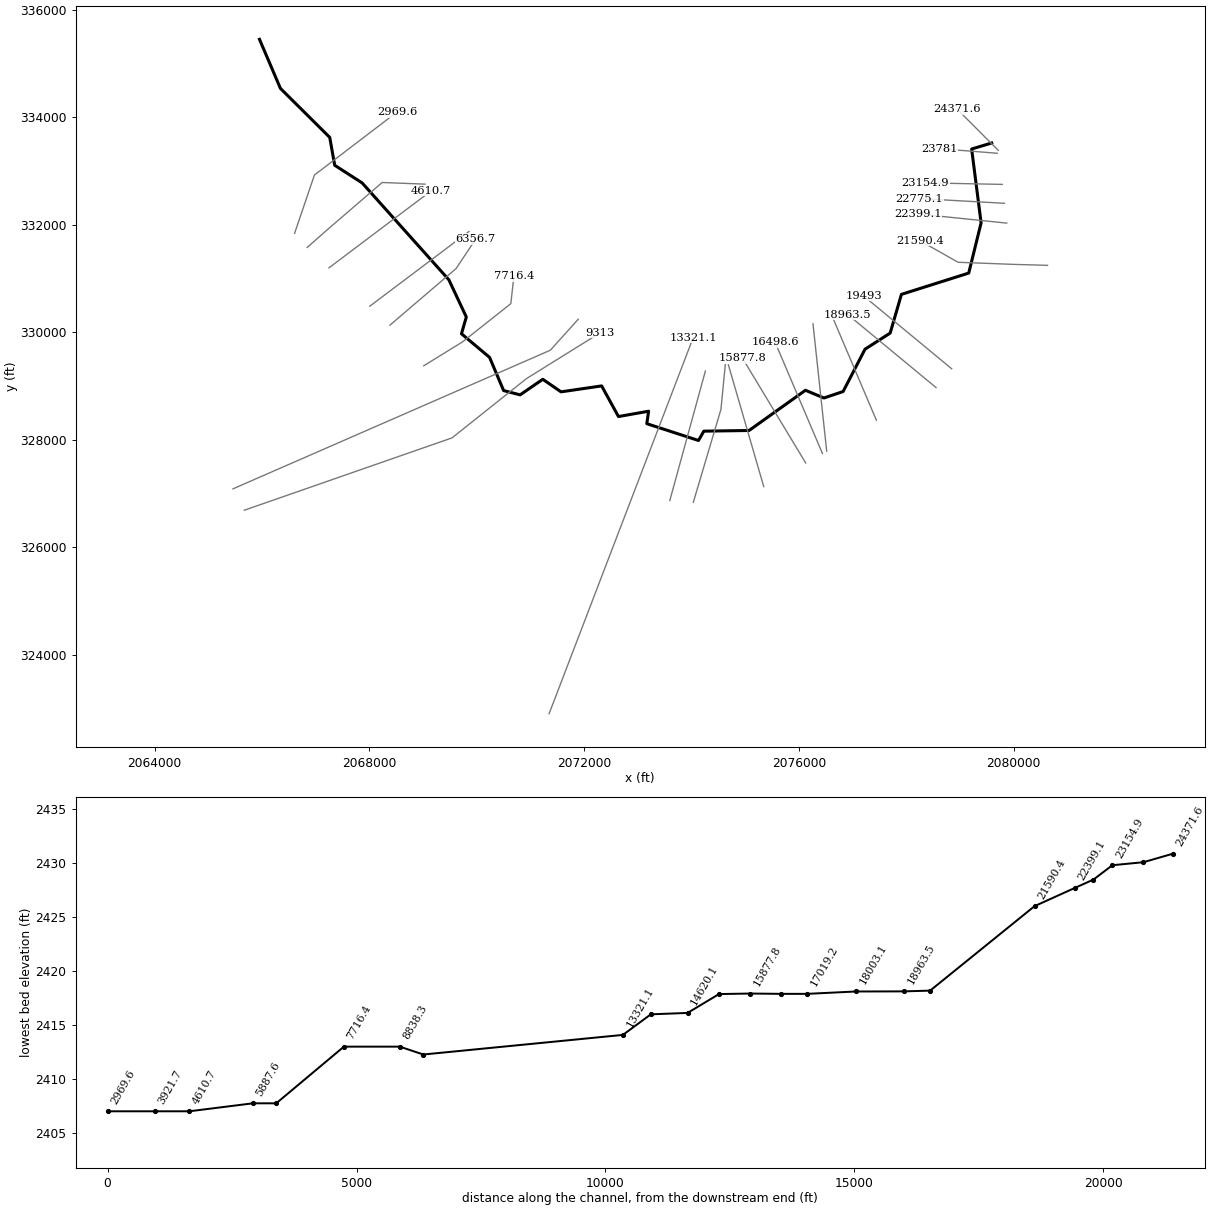
--- OtterCreek.prj (project) ---

Proj Title=OtterCreek
Current Plan=p01
Default Exp/Contr=0,0
English Units
Geom File=g01
Flow File=f01
Plan File=p01
BEGIN DESCRIPTION:
END DESCRIPTION:
DSS Export Rating Curves= 0
DSS Export Rating Curve Sorted= 0
DSS Export Volume Flow Curves= 0
DXF OffsetX= 0
DXF OffsetY= 0
DXF ScaleX= 0
DXF ScaleY= 0

--- OtterCreek.p01 (plan) ---

Plan Title=Floodplain
Program Version=4.00
Geom File=g01
Flow File=f01
K Sum by GR=0
Std Step Tol=0.01
Critical Tol=0.01
Num of Std Step Trials=20
Max Error Tol=0.3
Flow Tol Ratio=0.001
Split Flow NTrial=30
Split Flow Tol=0.02
Split Flow Ratio=0.02
Log Output Level=0
Friction Slope Method=1
Unsteady Friction Slope Method=2
Unsteady Bridges Friction Slope Method=1
Global Log Level=0
CheckData=False
Run HTab=0
Run UNet=0
Run PostProcess=0
UNET Theta=0
UNET Theta Warmup=0
UNET ZTol=0
UNET ZSATol=0
UNET MxIter=0
UNET MaxInSteps=0
UNET DtIC=0
UNET DtMin=0
UNET MaxCRTS=0
UNET WFStab=0
UNET SFStab=0
UNET WFX=0
UNET SFX=0
UNET DSS MLevel=0
UNET DZMax Abort=0
UNET Convert EG Bridges=0
UNET Use Existing IB Tables=0
UNET Froude Limit=0
UNET Froude Power=0
Write IC File=0
Echo Input=False
Echo Output=False
Write Detailed=0

--- OtterCreek.f01 (steady flow) ---

Flow Title=NFF Regression Equation
Program Version=4.00
Number of Profiles=1
Profile Names=P100yr
River Rch & RM=OtterCreek,Main      ,24371.6
521.2398
River Rch & RM=OtterCreek,Main      ,23154.9
529.4808
River Rch & RM=OtterCreek,Main      ,22399.1
584.3071
River Rch & RM=OtterCreek,Main      ,21590.4
719.0548
River Rch & RM=OtterCreek,Main      ,19493
745.6004
River Rch & RM=OtterCreek,Main      ,18963.5
1114.020
River Rch & RM=OtterCreek,Main      ,13882.1
1223.677
River Rch & RM=OtterCreek,Main      ,13321.1
1479.159
River Rch & RM=OtterCreek,Main      ,9313
1526.684
River Rch & RM=OtterCreek,Main      ,8838.3
1973.731
River Rch & RM=OtterCreek,Main      ,2969.6
2134.900
Boundary for River Rch & Prof#=OtterCreek,Main      ,1
Up Type=0
Dn Type=3
Dn Slope=0.000685

--- OtterCreek.g01 (geometry) ---

Geom Title=USGS 10m DEM
Program Version=4.10

River Reach=OtterCreek      ,Main
Reach XY= 30
     2079589.179      333518.341      2079215.74      333406.308
     2079391.831      332031.752     2079161.444      331097.659
     2077907.928       330701.62     2077698.553      329981.308
     2077229.803      329681.308      2076821.99      328893.807
     2076464.178      328773.495     2076120.428      328917.245
     2075070.428      328168.808      2074228.24      328156.308
      2074128.24       327982.87      2073165.74       328295.37
     2073199.594      328527.662     2072638.136      328428.183
     2072324.594      328998.235     2071568.344      328887.818
     2071228.761      329121.152     2070805.844      328831.568
     2070499.027      328911.711     2070237.094      329529.745
     2069714.004      329968.374     2069804.282      330280.527
     2069479.803      330971.933     2067864.956      332774.249
     2067352.803       333104.11     2067260.532      333622.454
     2066342.303      334533.912     2065951.837      335447.429

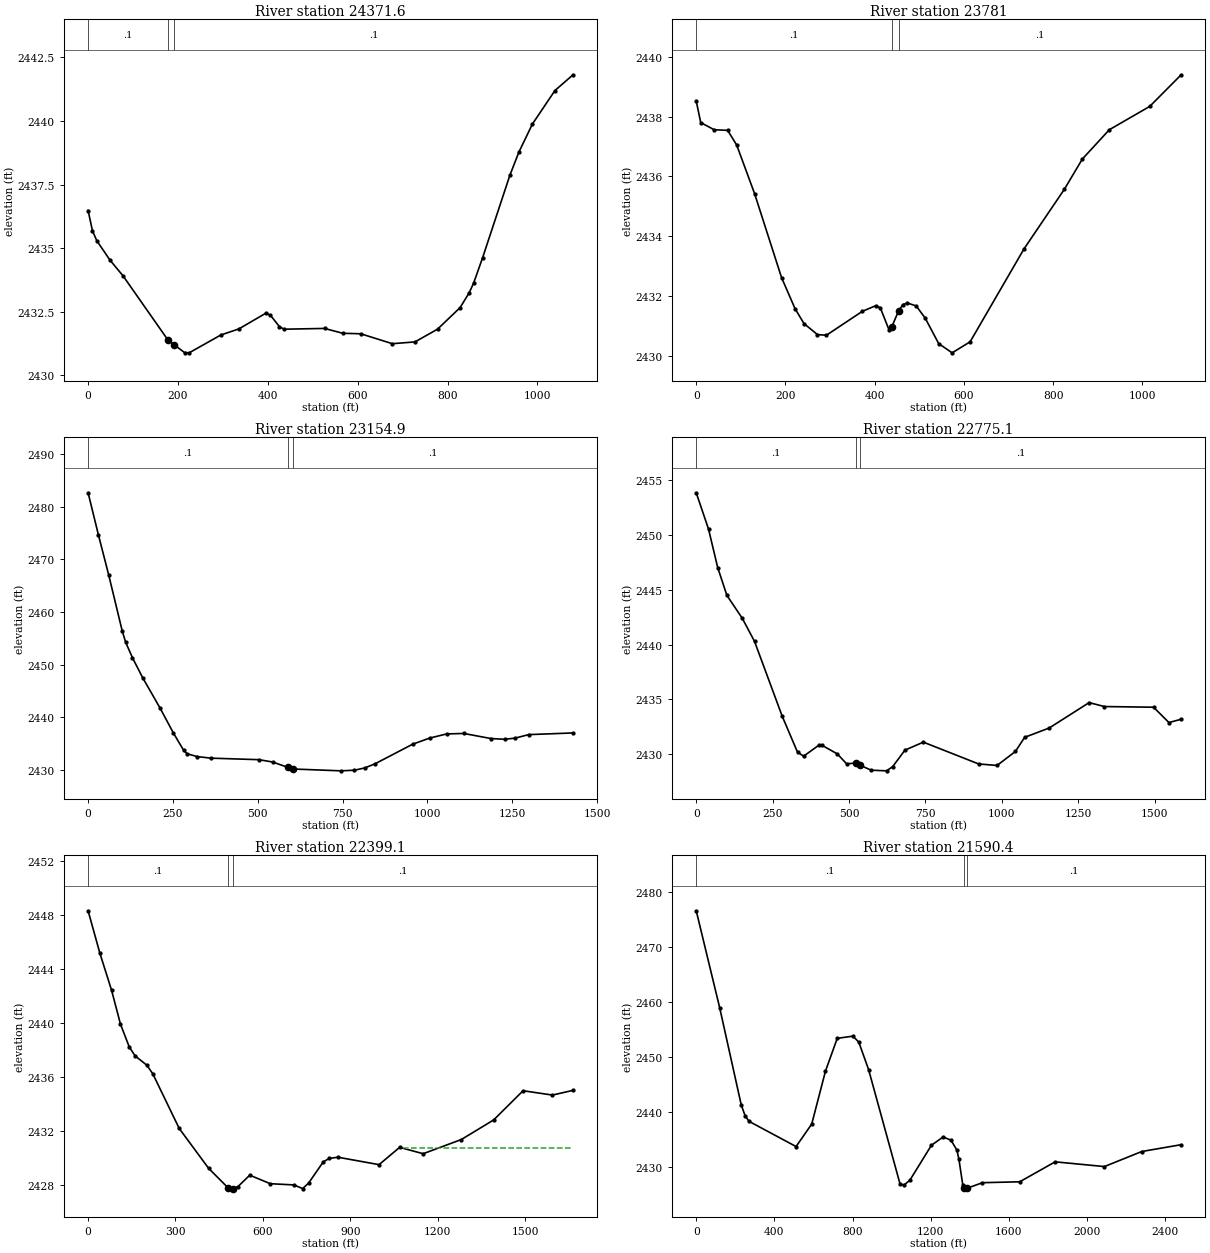
Type RM Length L Ch R = 1 ,24371.6 ,463,590.2,558
XS GIS Cut Line= 3
     2079712.621      333380.757     2079582.108       333511.27
     2078949.614      334143.764
#Sta/Elev= 30
       0 2436.48     9.7 2435.68    19.4 2435.29    48.6 2434.53    77.7 2433.91
   177.1  2431.4   192.1 2431.19   214.7 2430.89   224.8 2430.88   295.1 2431.58
   335.3 2431.82   395.6 2432.44   405.7 2432.36   425.8 2431.91   435.8 2431.81
   526.3 2431.84   566.5 2431.65   606.7 2431.63     677 2431.24   727.3 2431.31
   777.5 2431.81   827.8 2432.66   847.9 2433.24     858 2433.63     878 2434.63
   938.4 2437.86   958.4 2438.77   988.6 2439.88  1038.8  2441.2  1079.1 2441.82
#Mann= 3 , 0 , 0
       0      .1       0   177.1    .045       0   192.1      .1       0
Bank Sta=177.1,192.1
XS Rating Curve= 0 ,0
Exp/Cntr=0.3,0.1

Type RM Length L Ch R = 1 ,23781   ,623.6,625.1,628.4
XS GIS Cut Line= 2
     2079691.981      333327.093     2078608.748      333413.337
#Sta/Elev= 30
       0 2438.52    10.1  2437.8    40.2 2437.56    70.4 2437.54    90.6 2437.05
   130.8 2435.42   191.2 2432.61   221.4 2431.57   241.5 2431.07   271.7  2430.7
   291.8 2430.68   372.3 2431.48   402.5 2431.67   412.5  2431.6   432.6 2430.84
   438.3 2430.96   453.3 2431.49   462.8  2431.7   472.9 2431.76     493 2431.66
   513.2 2431.25   543.3  2430.4   573.5 2430.09   613.8 2430.46   734.5 2433.57
   825.1 2435.57   865.3 2436.58   925.7 2437.56  1016.2 2438.34  1086.7  2439.4
#Mann= 3 , 0 , 0
       0      .1       0   438.3    .045       0   453.3      .1       0
Bank Sta=438.3,453.3
XS Rating Curve= 0 ,0
Exp/Cntr=0.3,0.1

Type RM Length L Ch R = 1 ,23154.9 ,380.8,379.1,377.3
XS GIS Cut Line= 2
     2079785.322      332747.675     2078356.507      332776.736
#Sta/Elev= 30
       0 2482.63    30.2 2474.68    60.4  2467.1   100.6 2456.37   110.7 2454.23
   130.8 2451.28     161 2447.48   211.4 2441.81   251.6 2436.97   281.8 2433.68
   291.9 2433.05     322 2432.51   362.3 2432.22   503.2 2431.93   543.5 2431.49
   588.8 2430.47   603.8 2430.16   744.8 2429.81     785 2429.93   815.2 2430.36
   845.4 2431.14   956.1 2434.86  1006.4 2436.03  1056.7 2436.82  1107.1 2436.91
  1187.6 2435.94  1227.8 2435.81    1258 2436.02  1298.3 2436.69  1429.1 2437.01
#Mann= 3 , 0 , 0
       0      .1       0   588.8    .045       0   603.8      .1       0
Bank Sta=588.8,603.8
XS Rating Curve= 0 ,0
Exp/Cntr=0.3,0.1

Type RM Length L Ch R = 1 ,22775.1 ,374.9,375.7,377.2
XS GIS Cut Line= 2
     2079826.565      332396.219     2078241.966      332484.289
#Sta/Elev= 30
       0 2453.87    40.2 2450.56    70.3 2447.04   100.4  2444.5   150.7 2442.41
   190.8  2440.3   281.2 2433.48   331.5 2430.18   351.6 2429.82   401.8 2430.83
   411.8 2430.81     462 2430.02   492.2 2429.12     522 2429.19     537 2428.98
   572.5 2428.54   622.8 2428.48   642.8 2428.86     683 2430.37   743.3  2431.1
   924.1 2429.11   984.4 2428.97  1044.6 2430.25  1074.8 2431.54  1155.1 2432.39
  1285.7 2434.71  1335.9 2434.35  1496.6 2434.29  1546.9 2432.89    1587 2433.19
#Mann= 3 , 0 , 0
       0      .1       0     522    .045       0     537      .1       0
Bank Sta=522,537
XS Rating Curve= 0 ,0
Exp/Cntr=0.3,0.1

Type RM Length L Ch R = 1 ,22399.1 ,806.7,808.6,810.8
XS GIS Cut Line= 2
      2079869.85      332027.353     2078213.719      332197.649
#Sta/Elev= 30
       0 2448.28    40.4 2445.14    80.7 2442.39     111  2439.9   141.3  2438.2
   161.4 2437.54   201.8 2436.85     222 2436.22   312.8 2432.17   413.7 2429.22
   481.2 2427.76   494.4  2427.7   496.2 2427.71   514.6 2427.87     555 2428.71
   625.6 2428.08   706.3 2427.99   736.6 2427.72   756.8 2428.12   807.2 2429.69
   827.4 2429.95   857.7 2430.04   998.9 2429.49  1069.6 2430.77  1150.3  2430.3
  1281.4 2431.35  1392.4  2432.8  1493.3 2434.96  1594.2 2434.64  1664.9 2434.99
#Mann= 3 , 0 , 0
       0      .1       0   481.2    .045       0   496.2      .1       0
#XS Ineff= 2 , 0
                         1082.55          2430.7
Permanent Ineff=
       F       F
Bank Sta=481.2,496.2
XS Rating Curve= 0 ,0
Exp/Cntr=0.3,0.1

Type RM Length L Ch R = 1 ,21590.4 ,2112.5,2097.2,2081.9
XS GIS Cut Line= 4
      2080628.77      331241.564     2079997.668      331259.523
     2078963.867      331298.581     2078253.344      331700.519
#Sta/Elev= 30
       0 2476.58   120.3 2458.91   230.5 2441.26   250.5 2439.28   270.6 2438.28
   511.1  2433.7   591.3  2437.8   661.5 2447.41   721.8 2453.38   802.1 2453.78
   832.2 2452.69   882.5 2447.67  1043.2  2426.9  1063.2 2426.69  1093.4 2427.57
  1203.9 2433.94  1264.1 2435.45  1304.3 2434.85  1334.4 2433.04  1344.5 2431.41
  1364.6 2426.67  1371.9 2426.19  1374.6 2426.01  1386.9 2426.12    1465 2427.13
  1655.8 2427.29  1837.2 2430.92  2089.2 2430.06  2280.7  2432.8  2482.2 2434.04
#Mann= 3 , 0 , 0
       0      .1       0  1371.9    .045       0  1386.9      .1       0
Bank Sta=1371.9,1386.9
XS Rating Curve= 0 ,0
Exp/Cntr=0.3,0.1

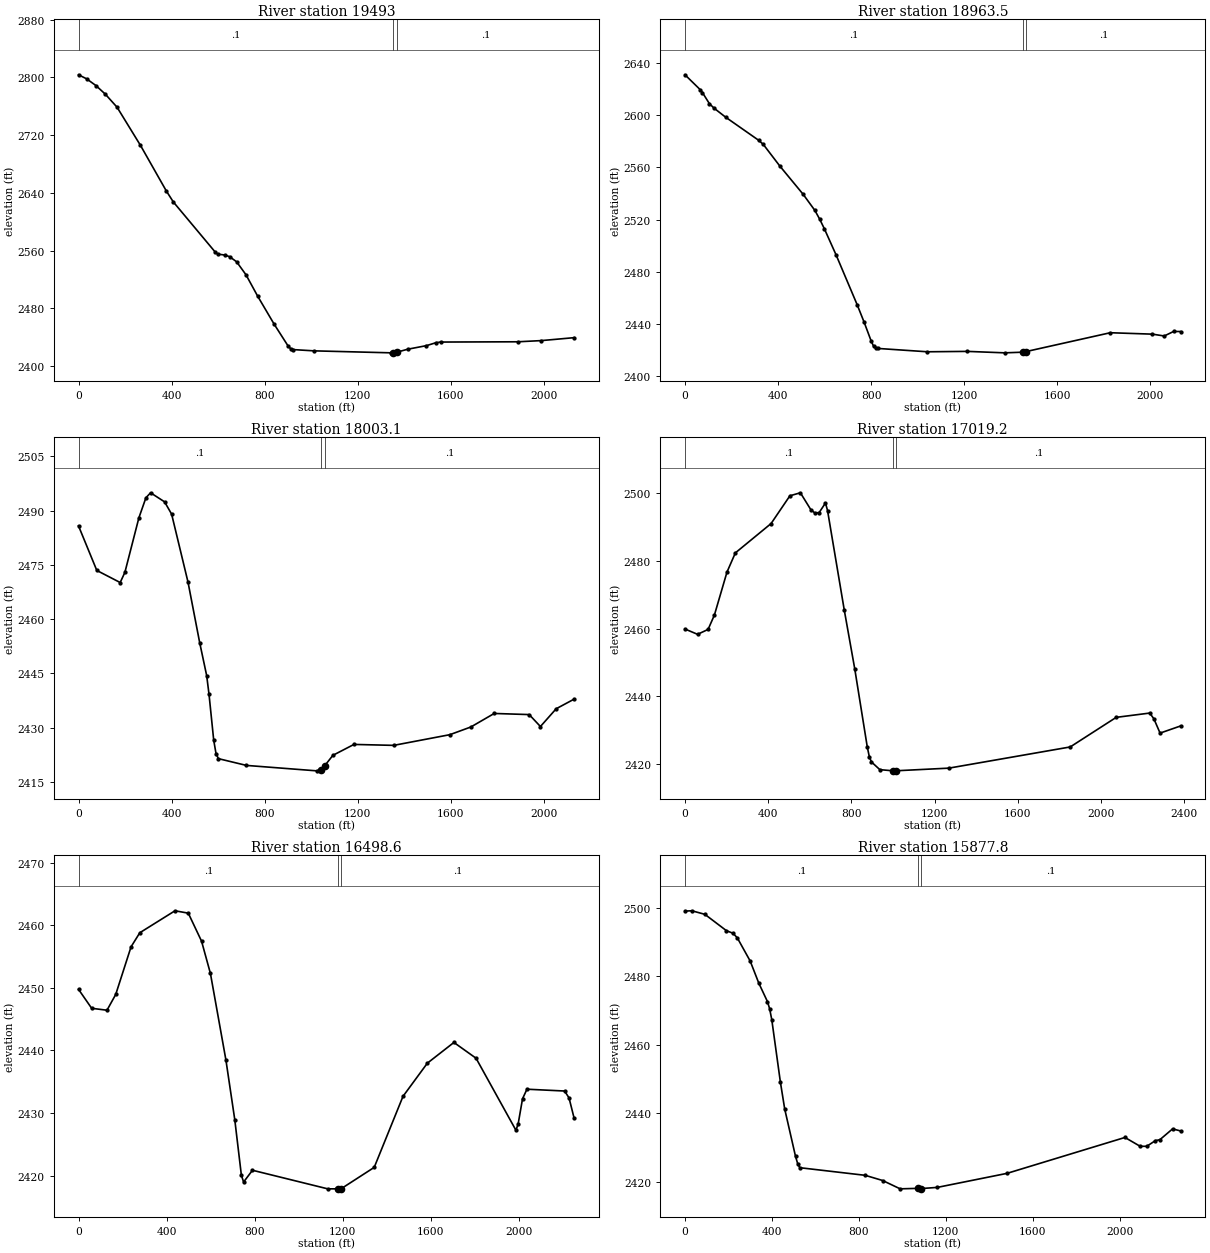
Type RM Length L Ch R = 1 ,19493   ,528.9,529.3,530.8
XS GIS Cut Line= 3
     2078844.689      329316.759     2078841.298      329319.559
     2077202.526      330672.938
#Sta/Elev= 30
       0 2803.73    34.6 2798.16    74.9 2788.77   115.2 2776.85   165.6 2758.76
   266.3  2705.8   377.1 2642.75   407.3 2627.43   588.6 2557.44   598.7 2555.08
   628.9 2553.73   649.1 2551.55   679.3 2544.45   719.6 2526.43   769.9 2496.69
   840.4 2458.05   900.9 2427.48     911 2424.11     921 2422.69  1011.7 2420.93
  1344.1 2418.17  1352.5 2418.25  1367.5 2419.01  1414.6  2423.2  1495.2 2428.16
  1535.5 2432.18  1555.6 2433.13    1888  2433.5  1988.8 2435.14  2129.8 2439.22
#Mann= 3 , 0 , 0
       0      .1       0  1352.5    .045       0  1367.5      .1       0
Bank Sta=1352.5,1367.5
XS Rating Curve= 0 ,0
Exp/Cntr=0.3,0.1

Type RM Length L Ch R = 1 ,18963.5 ,971.2,960,958.3
XS GIS Cut Line= 3
     2078552.448      328967.693     2078549.057      328970.494
     2076910.285      330323.873
#Sta/Elev= 30
       0 2630.91    64.8 2619.63    74.9 2617.32   105.1 2608.76   125.3  2605.3
   175.6 2598.33   316.7 2580.77   336.8 2577.56   407.3 2561.12     508 2539.38
   558.4 2527.04   578.6 2520.48   598.7 2513.15   649.1 2493.14   739.7    2455
   769.9 2441.51   800.2 2427.08   810.2 2423.24   820.3 2421.76   830.4 2421.45
  1041.9 2418.91  1213.1 2419.21  1374.3  2418.1  1451.8  2418.6  1466.8 2419.12
  1827.6 2433.49  2008.9  2432.4  2059.3    2431  2099.6 2434.46  2129.8 2434.41
#Mann= 3 , 0 , 0
       0      .1       0  1451.8    .045       0  1466.8      .1       0
Bank Sta=1451.8,1466.8
XS Rating Curve= 0 ,0
Exp/Cntr=0.3,0.1

Type RM Length L Ch R = 1 ,18003.1 ,989.3,984.2,977.6
XS GIS Cut Line= 4
      2077441.54      328359.935     2077410.699      328432.358
     2076685.989      330134.172      2076606.43         330321.
#Sta/Elev= 30
       0  2485.8    78.7 2473.48   179.2 2470.14   199.4 2472.95   259.7 2488.04
   289.8 2493.56   309.9 2494.95   370.2 2492.44   400.4 2489.05   470.8 2470.28
     521 2453.55   551.2  2444.4   561.2 2439.26   581.4 2426.56   591.4 2422.84
   601.5 2421.46   722.1 2419.59  1023.7 2418.09  1043.2 2418.29  1058.2 2419.46
    1094 2422.38  1184.5 2425.39  1355.4 2425.13  1596.7 2428.08  1687.2 2430.21
  1787.7 2433.95  1938.1 2433.64  1986.4 2430.34  2054.1 2435.25  2131.5 2437.92
#Mann= 3 , 0 , 0
       0      .1       0  1043.2    .045       0  1058.2      .1       0
Bank Sta=1043.2,1058.2
XS Rating Curve= 0 ,0
Exp/Cntr=0.3,0.1

Type RM Length L Ch R = 1 ,17019.2 ,517.9,519.9,526.5
XS GIS Cut Line= 4
     2076516.146      327785.106     2076471.801      328196.534
     2076273.582      330035.578     2076260.872      330153.497
#Sta/Elev= 30
       0 2459.85    60.6 2458.28     111 2459.73   141.3 2463.96   201.9 2476.71
   242.2 2482.39   413.8 2491.07   504.3 2499.29   554.6 2500.18   604.8 2495.18
   624.9 2494.16     645 2494.34   675.2 2497.16   685.2 2494.91   765.7 2465.41
   815.9 2448.07   876.2 2424.91   886.3 2421.94   896.3 2420.49   936.6 2418.22
   999.5 2417.88  1006.9 2417.87  1014.5 2417.89  1268.3 2418.67  1851.4 2424.94
  2072.5  2433.7  2233.4 2434.97  2253.4 2433.29  2283.3 2429.04  2382.1 2431.16
#Mann= 3 , 0 , 0
       0      .1       0   999.5    .045       0  1014.5      .1       0
Bank Sta=999.5,1014.5
XS Rating Curve= 0 ,0
Exp/Cntr=0.3,0.1

Type RM Length L Ch R = 1 ,16498.6 ,616.6,620.6,624
XS GIS Cut Line= 4
     2076436.895      327740.418     2076288.856      328088.054
     2075564.146      329789.868     2075555.003      329811.339
#Sta/Elev= 30
       0 2449.75    59.7 2446.72   129.3 2446.41     169 2448.93   238.6 2456.54
   278.4 2458.79   438.2  2462.3   498.5 2461.92   558.8 2457.44     599 2452.29
   669.4 2438.46   709.6 2428.93   739.7 2420.02   749.8 2418.96     790 2420.84
  1131.8 2417.87  1179.1 2417.87  1194.1 2417.92  1342.9  2421.3  1473.6 2432.65
  1584.2 2437.95  1704.8 2441.26  1805.3 2438.74  1986.3 2427.24  1996.3 2428.19
  2016.4 2432.26  2036.5 2433.79  2207.4  2433.5  2227.5 2432.41  2250.9 2429.13
#Mann= 3 , 0 , 0
       0      .1       0  1179.1    .045       0  1194.1      .1       0
Bank Sta=1179.1,1194.1
XS Rating Curve= 0 ,0
Exp/Cntr=0.3,0.1

Type RM Length L Ch R = 1 ,15877.8 ,632.5,626.7,620.8
XS GIS Cut Line= 5
     2076124.879       327564.48     2076123.769      327566.319
     2075841.603      328033.657     2074975.083      329468.835
     2074946.405      329516.332
#Sta/Elev= 30
       0  2499.1    31.9 2499.19    91.5 2498.15   190.7 2493.37   220.5 2492.63
   240.4 2491.31   299.9  2484.5   339.6 2478.03   379.3 2472.65   389.2  2470.6
   399.2 2467.39   438.9  2449.1   458.7 2441.25   508.4 2427.42   518.3 2425.29
   528.2 2424.08   829.2 2421.85   909.5 2420.33   989.8  2417.9  1071.1 2418.04
  1086.1 2417.98  1160.4 2418.32  1481.7 2422.43  2023.8 2432.92    2094 2430.33
  2124.2 2430.34  2164.3 2432.01  2184.4 2432.26    2243 2435.43    2280 2434.82
#Mann= 3 , 0 , 0
       0      .1       0  1071.1    .045       0  1086.1      .1       0
Bank Sta=1071.1,1086.1
XS Rating Curve= 0 ,0
Exp/Cntr=0.3,0.1

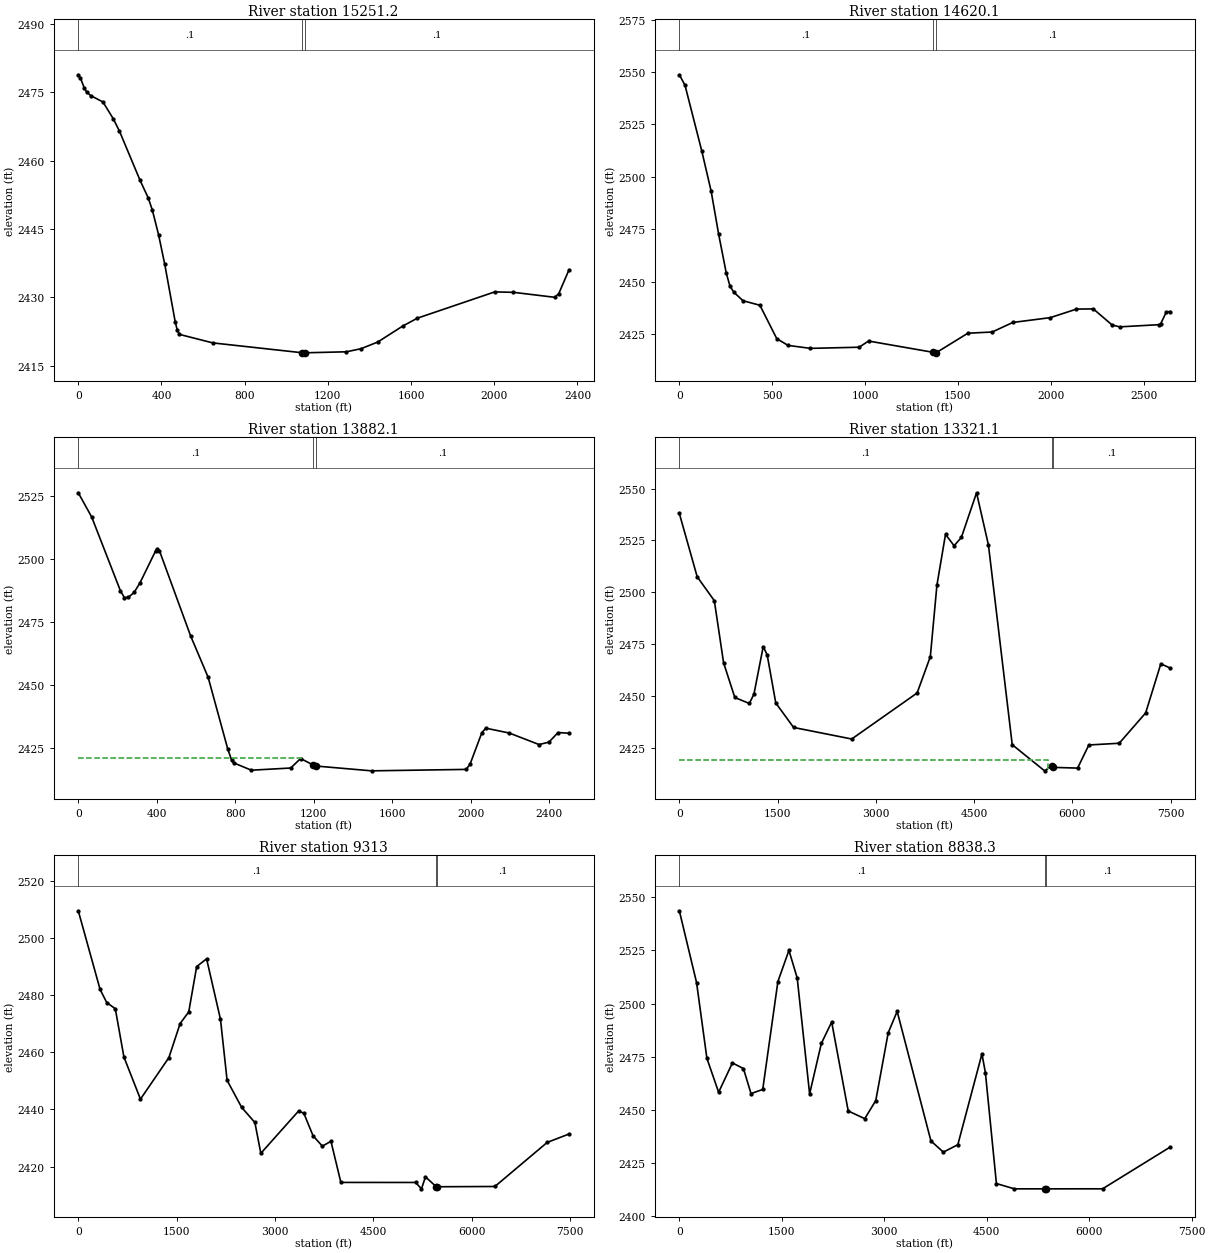
Type RM Length L Ch R = 1 ,15251.2 ,646.1,631.1,616
XS GIS Cut Line= 4
     2075343.796      327124.045     2075236.137       327494.59
     2074768.388      329104.498      2074685.48      329389.853
#Sta/Elev= 30
       0 2478.87     9.9 2478.21    29.7 2475.89    39.6 2475.13    59.4 2474.31
   118.7  2472.9   168.2 2469.23   197.9 2466.52   296.8 2455.74   336.4 2451.84
   356.2 2449.17   385.9 2443.81     416 2437.24   466.2 2424.63   476.2  2422.8
   486.3  2421.9   646.9 2420.03  1076.8 2417.87  1078.6 2417.85  1091.8 2417.86
  1289.4 2418.08  1359.6 2418.76  1439.9 2420.22  1560.4 2423.74  1630.7 2425.46
  2002.1 2431.22  2092.1 2431.13  2290.2 2430.04    2310 2430.82  2359.5 2436.07
#Mann= 3 , 0 , 0
       0      .1       0  1076.8    .045       0  1091.8      .1       0
Bank Sta=1076.8,1091.8
XS Rating Curve= 0 ,0
Exp/Cntr=0.3,0.1

Type RM Length L Ch R = 1 ,14620.1 ,736.4,738,745
XS GIS Cut Line= 3
     2074031.554        326831.7      2074546.55      328562.319
     2074628.068      329395.065
#Sta/Elev= 30
       0 2548.65    30.3 2543.72     121 2512.27   171.5 2493.05   211.8  2472.6
   252.2 2454.35   272.4 2447.99   292.5 2445.07     343 2440.93   433.8 2438.79
   524.5 2422.87   585.1 2419.65   706.1 2418.23   968.4 2418.78  1018.8 2421.73
  1366.4 2416.35  1381.4 2416.11    1382  2416.1  1553.4 2425.45  1684.6 2426.03
  1795.5 2430.58  1997.2 2432.88  2138.3 2436.95    2229 2437.05  2329.8 2429.42
  2370.2 2428.48  2581.9 2429.52  2591.9 2429.97  2622.2 2435.57  2642.4  2435.8
#Mann= 3 , 0 , 0
       0      .1       0  1366.4    .045       0  1381.4      .1       0
#XS Ineff= 2 , 0
         1020.37 2421.55
Permanent Ineff=
       F       F
Bank Sta=1366.4,1381.4
XS Rating Curve= 0 ,0
Exp/Cntr=0.3,0.1

Type RM Length L Ch R = 1 ,13882.1 ,563.1,560.9,558.7
XS GIS Cut Line= 5
     2073593.969      326865.096     2073643.088      327043.738
     2073787.819      327570.116     2074232.284      329186.608
     2074256.851      329275.956
#Sta/Elev= 30
       0 2526.26    68.3 2516.66     215 2487.35   234.9 2484.71   254.8 2484.76
   284.5 2486.73   314.3 2490.51   393.7 2503.16   403.6 2503.94   413.6 2503.27
   572.4 2469.49   661.7 2453.07   761.3 2424.73   781.4 2420.18   791.4 2419.15
   881.8 2416.22  1082.5 2417.09  1132.7 2420.86  1195.6 2418.33  1210.6 2417.88
  1494.1 2415.97    1976 2416.54  1996.1  2418.6  2056.3 2431.12  2076.4 2432.89
  2196.8 2430.95  2347.4  2426.4  2397.6 2427.34  2444.7 2431.16  2500.3 2430.88
#Mann= 3 , 0 , 0
       0      .1       0  1195.6    .045       0  1210.6      .1       0
#XS Ineff= 2 , 0
         1134.63 2420.91
Permanent Ineff=
       F       F
Bank Sta=1195.6,1210.6
XS Rating Curve= 0 ,0
Exp/Cntr=0.3,0.1

Type RM Length L Ch R = 1 ,13321.1 ,4024.4,4009.1,3949.8
XS GIS Cut Line= 2
     2071345.733      322898.367     2074028.768      329894.437
#Sta/Elev= 30
       0 2538.01   272.3 2507.53   534.5 2495.97   675.7 2466.09   847.1 2449.38
    1069 2446.49  1139.6 2451.04  1280.8  2473.9  1341.3 2469.89  1472.4 2446.74
  1744.6 2434.95  2632.1 2429.39  3630.5 2451.54  3832.2 2469.03    3933 2503.47
  4064.1 2527.93  4195.2 2522.44  4306.2 2526.44  4538.1 2547.95  4719.6 2522.78
  5082.7 2426.65  5576.8 2414.06    5688  2416.5    5703 2415.73    6081 2415.38
  6252.5 2426.52  6716.4 2427.34  7119.8 2441.94  7351.7 2465.61  7492.9 2463.56
#Mann= 3 , 0 , 0
       0      .1       0    5688    .045       0    5703      .1       0
#XS Ineff= 2 , 0
         5626.22 2419.29
Permanent Ineff=
       F       F
Bank Sta=5688,5703
XS Rating Curve= 0 ,0
Exp/Cntr=0.3,0.1

Type RM Length L Ch R = 1 ,9313    ,485.2,473.3,462.6
XS GIS Cut Line= 4
     2065669.627      326685.233     2069538.207      328031.275
     2070926.351      329135.295     2072298.259      329987.665
#Sta/Elev= 30
       0 2509.42   332.9 2481.92   433.8 2477.35     565 2475.19   696.1 2458.32
   948.4 2443.59  1382.2 2458.11  1553.7 2470.02  1684.8 2474.06  1805.9 2489.92
  1957.2 2492.63  2169.1 2471.48    2270 2450.15  2491.9 2440.71  2693.7 2435.43
  2784.5 2424.65  3359.6 2439.42  3440.3 2438.67  3581.5 2430.76  3722.8 2427.16
  3853.9 2428.85  4005.3 2414.48  5144.1 2414.47  5234.8 2412.24  5295.3 2416.44
  5459.7 2412.97  5474.7 2412.97  6354.2 2413.06  7151.7 2428.46  7484.8  2431.4
#Mann= 3 , 0 , 0
       0      .1       0  5459.7    .045       0  5474.7      .1       0
#XS Ineff= 2 , 0
         5300.27 2416.32
Permanent Ineff=
       F       F
Bank Sta=5459.7,5474.7
XS Rating Curve= 0 ,0
Exp/Cntr=0.3,0.1

Type RM Length L Ch R = 1 ,8838.3  ,1099.7,1121.7,1129.3
XS GIS Cut Line= 4
     2065458.565      327083.005     2071369.007       329662.27
     2071860.953      330207.883     2071888.842      330238.814
#Sta/Elev= 30
       0 2543.54   252.3 2509.81   403.6 2474.24   575.2 2458.32     777  2472.1
   938.5 2469.44  1049.5 2457.69    1221 2459.66    1443 2510.33  1604.5 2524.94
  1725.6 2511.96  1907.2 2457.56  2078.7 2481.23  2230.1  2491.3  2472.3 2449.54
  2714.5 2445.92  2875.9 2454.44  3057.6 2486.24  3188.8  2496.3  3683.2 2435.46
  3864.8 2430.21  4076.8 2433.68  4429.9 2476.32  4480.4 2467.54  4641.8 2415.45
  4904.2 2412.97    5354 2412.97    5369 2412.97  6195.9 2412.98  7184.1 2432.56
#Mann= 3 , 0 , 0
       0      .1       0    5354    .045       0    5369      .1       0
Bank Sta=5354,5369
XS Rating Curve= 0 ,0
Exp/Cntr=0.3,0.1

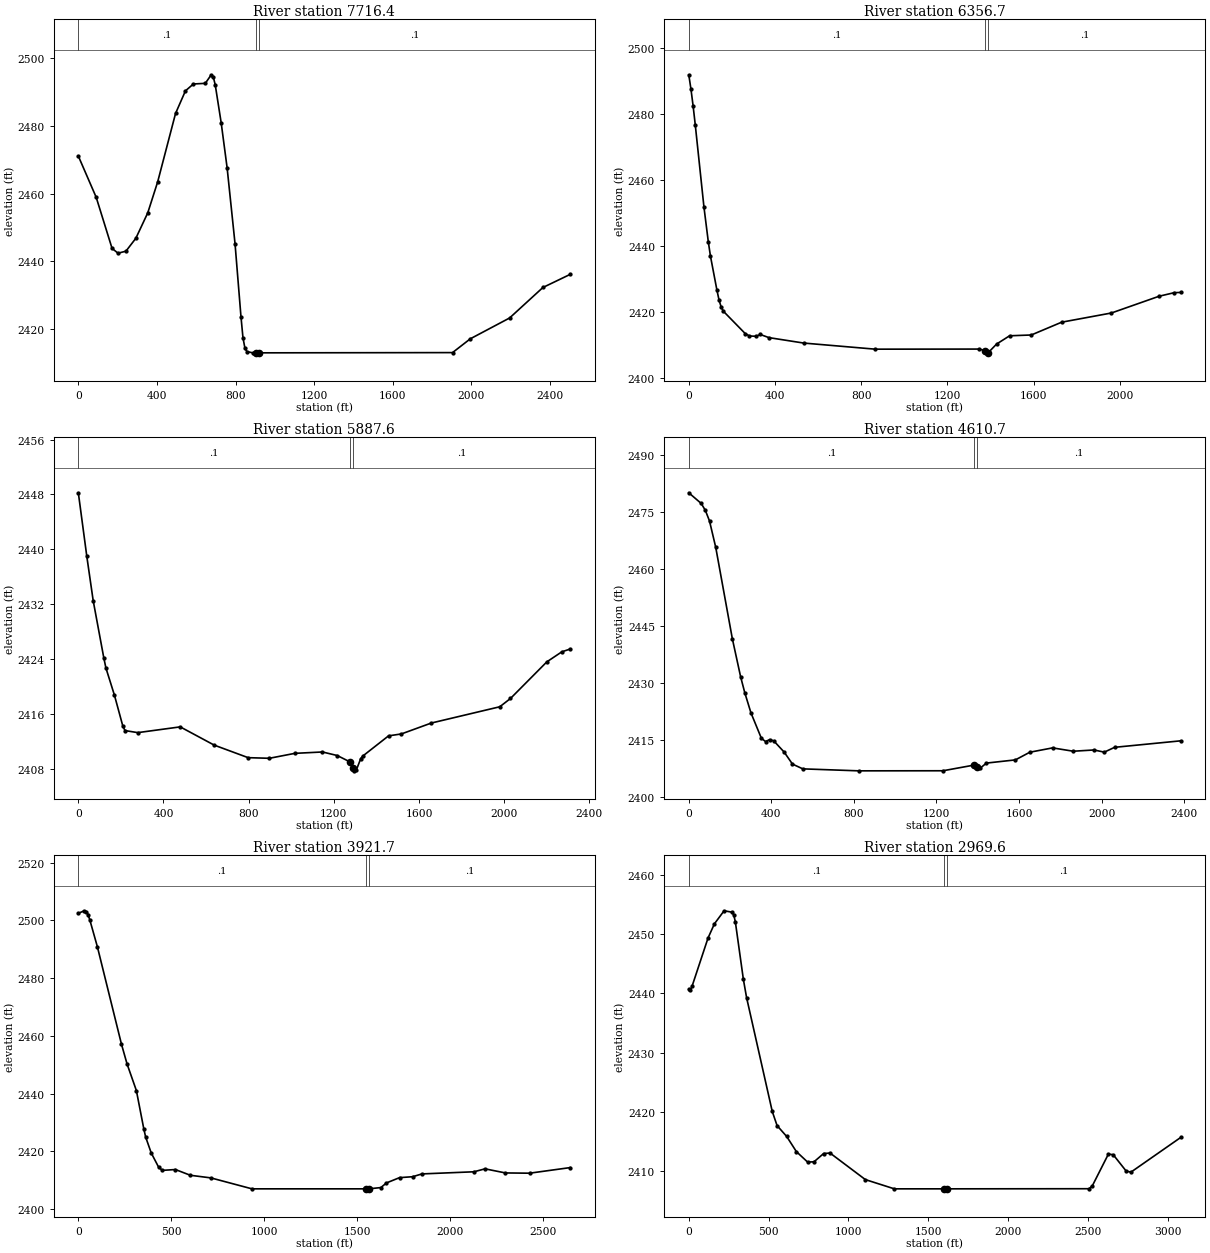
Type RM Length L Ch R = 1 ,7716.4  ,1356.3,1359.5,1361.2
XS GIS Cut Line= 4
     2069012.254      329373.116     2069734.339      329817.753
     2070633.665      330529.328     2070689.278        331035.4
#Sta/Elev= 30
       0 2471.11    90.9 2458.93   171.6 2443.84   201.9 2442.41   242.3 2443.01
   292.8 2446.83   353.3 2454.33   403.8  2463.5   494.7  2483.7   545.1 2490.38
   585.5 2492.41   646.1  2492.6   676.4 2495.13   686.5 2494.55   696.6 2492.19
   726.9 2480.96   757.2 2467.63   797.5 2445.19   827.8 2423.55   837.9 2417.38
     848  2414.3   858.1 2413.34   888.2 2412.97   903.1 2412.97   918.1 2412.97
  1904.3 2413.04  1994.8 2417.12  2194.4 2423.26  2364.2 2432.28  2503.9 2436.18
#Mann= 3 , 0 , 0
       0      .1       0   903.1    .045       0   918.1      .1       0
Bank Sta=903.1,918.1
XS Rating Curve= 0 ,0
Exp/Cntr=0.3,0.1

Type RM Length L Ch R = 1 ,6356.7  ,470.1,469.1,468.2
XS GIS Cut Line= 3
     2068382.029      330128.836     2069612.985      331180.737
     2069981.116      331732.796
#Sta/Elev= 30
       0 2491.84    10.1  2487.5    20.1 2482.44    30.2 2476.64    70.4 2451.82
    90.5 2441.36   100.6 2436.97   130.7 2426.64   140.8 2423.57   150.9 2421.45
   160.9 2420.27   261.5 2413.56   281.6 2412.81   311.8 2412.72   331.9 2413.26
   372.1 2412.31     533 2410.67   864.9 2408.82  1347.6 2408.85  1374.3 2408.39
  1387.9 2407.71  1389.3 2407.77  1428.1 2410.37  1488.4 2412.87    1589 2413.11
  1729.8 2416.98    1961 2419.77  2182.2 2424.84  2252.6 2425.92  2282.7 2425.98
#Mann= 3 , 0 , 0
       0      .1       0  1374.3    .045       0  1389.3      .1       0
Bank Sta=1374.3,1389.3
XS Rating Curve= 0 ,0
Exp/Cntr=0.3,0.1

Type RM Length L Ch R = 1 ,5887.6  ,1276.7,1276.7,1257.7
XS GIS Cut Line= 4
     2068006.367      330481.181     2068587.936      330918.935
     2069026.055      331248.712     2069852.826      331871.031
#Sta/Elev= 30
       0 2448.25    39.9 2438.96    69.8 2432.52   119.7 2424.17   129.6  2422.7
   169.5 2418.75   209.4 2414.19   219.4 2413.58   279.2 2413.28   478.6 2414.12
   638.2 2411.46   797.7 2409.63   897.4 2409.54    1017 2410.26  1146.7 2410.46
  1216.4 2409.94  1276.1 2409.01  1291.1  2408.1  1296.4 2407.71  1306.4 2407.88
  1326.5  2409.5  1336.6 2409.88  1457.1 2412.81  1517.4 2413.09    1658 2414.68
  1979.5 2417.05  2029.8 2418.26  2200.6  2423.6  2270.9 2425.06  2311.1 2425.48
#Mann= 3 , 0 , 0
       0      .1       0  1276.1    .045       0  1291.1      .1       0
Bank Sta=1276.1,1291.1
XS Rating Curve= 0 ,0
Exp/Cntr=0.3,0.1

Type RM Length L Ch R = 1 ,4610.7  ,687.6,688.6,688.5
XS GIS Cut Line= 4
     2067245.764      331194.574     2067767.574      331587.345
     2068205.693      331917.122     2069150.233      332628.088
#Sta/Elev= 30
       0 2480.14    60.3 2477.33    80.4  2475.5   100.5 2472.71   130.6 2465.78
     211 2441.75   251.2 2431.72   271.3 2427.53   301.4  2422.2   351.7 2415.54
   371.8 2414.68   391.9 2415.19     412 2414.84   462.2  2411.9   502.4 2408.74
   552.6 2407.49   822.6 2406.97  1231.5 2406.99  1381.6 2408.48  1396.6 2408.11
  1411.9 2407.67  1441.9 2409.01  1582.2 2409.85  1652.3 2411.87  1762.5 2413.01
  1862.7 2412.13  1962.9 2412.46    2013 2411.89  2063.1 2413.16  2383.7 2414.87
#Mann= 3 , 0 , 0
       0      .1       0  1381.6    .045       0  1396.6      .1       0
Bank Sta=1381.6,1396.6
XS Rating Curve= 0 ,0
Exp/Cntr=0.3,0.1

Type RM Length L Ch R = 1 ,3921.7  ,951.8,952.3,970.7
XS GIS Cut Line= 5
     2066840.199      331574.966     2066856.798      331589.538
      2067254.96      331939.082      2068237.59      332782.911
     2069034.731      332752.544
#Sta/Elev= 30
       0 2502.45    32.1 2503.32    42.1 2503.06    52.1 2502.03    62.1 2500.07
   102.1 2490.92     232 2457.06     262 2450.23     312 2441.03     352 2427.73
     362 2424.89     392 2419.38     432 2414.43     452 2413.37   521.9 2413.66
   602.1 2411.67   712.6 2410.76   933.4 2406.97  1546.1 2406.97  1561.1 2406.97
  1626.2 2407.41  1656.4 2409.02  1726.6 2410.85  1796.9 2411.17  1847.1 2412.14
  2126.3 2412.88  2186.2  2413.9  2295.8 2412.48  2425.5 2412.39  2644.9 2414.34
#Mann= 3 , 0 , 0
       0      .1       0  1546.1    .045       0  1561.1      .1       0
Bank Sta=1546.1,1561.1
XS Rating Curve= 0 ,0
Exp/Cntr=0.3,0.1

Type RM Length L Ch R = 1 ,2969.6  ,2969.9,2968.5,2967.9
XS GIS Cut Line= 3
     2066605.592      331835.904     2066975.184      332921.513
     2068515.044      334095.137
#Sta/Elev= 30
       0 2440.69    10.1 2440.54    20.1 2441.18   120.7 2449.38     161 2451.79
   221.3 2453.98   271.6 2453.74   281.7 2453.29   291.7 2452.13     342  2442.4
   362.2  2439.3   523.1 2420.05   553.3 2417.66   613.6 2415.82     674 2413.27
   744.4  2411.5   784.6 2411.54     845 2412.94   885.2 2413.02  1106.6 2408.53
    1288 2406.97    1602 2406.97    1617 2406.97  2508.1 2406.99  2528.3 2407.47
  2629.1 2412.84  2659.4 2412.74  2740.1 2409.99  2770.3 2409.79  3082.9 2415.67
#Mann= 3 , 0 , 0
       0      .1       0    1602    .045       0    1617      .1       0
Bank Sta=1602,1617
XS Rating Curve= 0 ,0
Exp/Cntr=0.3,0.1

Chan Stop Cuts=-1
Use User Specified Reach Order=0
Composite Channel Slope=5